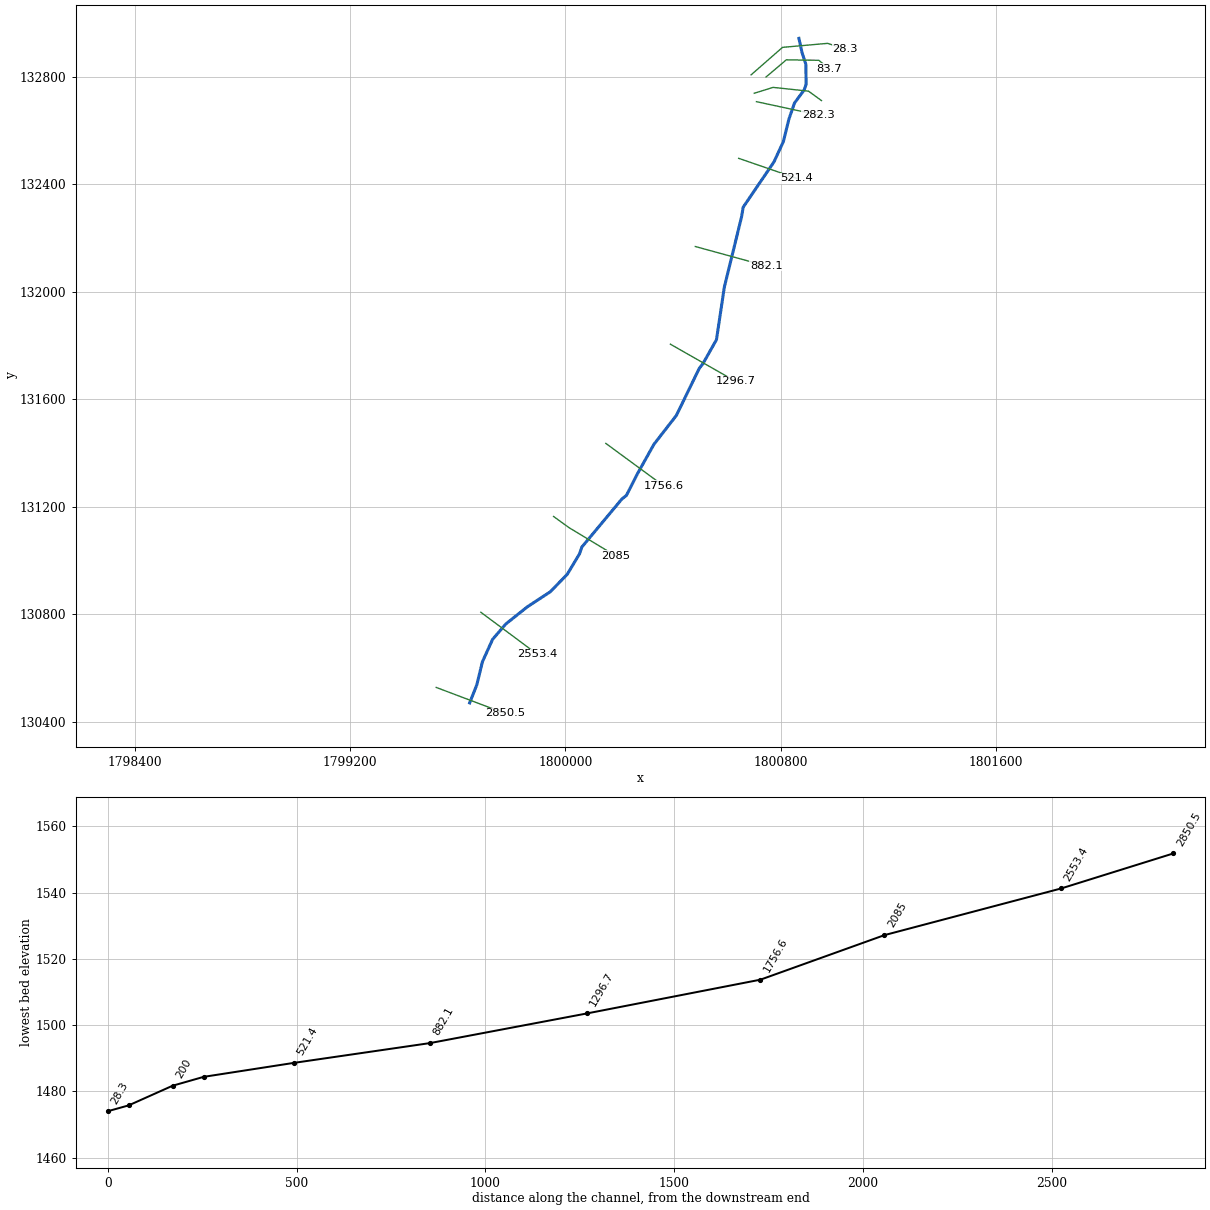
--- Left Fork Mill Creek.prj (project) ---

Proj Title=Left Fork Mill Creek
Current Plan=p01
Geom File=g01
Flow File=f01
Plan File=p01
DSS Export Rating Curves=0
DSS Export Rating Curve Sorted=0
DSS Export Volume Flow Curves=0
DXF OffsetX=0
DXF OffsetY=0
DXF ScaleX=0
DXF ScaleY=0

--- Left Fork Mill Creek.p01 (plan) ---

Plan Title=Floodplain
Program Version=4.00
Geom File=g01
Flow File=f01
K Sum by GR=0
Std Step Tol=0.01
Critical Tol=0.01
Num of Std Step Trials=20
Max Error Tol=0.3
Flow Tol Ratio=0.001
Split Flow NTrial=30
Split Flow Tol=0.02
Split Flow Ratio=0.02
Log Output Level=0
Friction Slope Method=1
Unsteady Friction Slope Method=2
Unsteady Bridges Friction Slope Method=1
Global Log Level=0
CheckData=False
Run HTab=0
Run UNet=0
Run PostProcess=0
UNET Theta=0
UNET Theta Warmup=0
UNET ZTol=0
UNET ZSATol=0
UNET MxIter=0
UNET MaxInSteps=0
UNET DtIC=0
UNET DtMin=0
UNET MaxCRTS=0
UNET WFStab=0
UNET SFStab=0
UNET WFX=0
UNET SFX=0
UNET DSS MLevel=0
UNET DZMax Abort=0
UNET Convert EG Bridges=0
UNET Use Existing IB Tables=0
UNET Froude Limit=0
UNET Froude Power=0
Write IC File=0
Echo Input=False
Echo Output=False
Write Detailed=0

--- Left Fork Mill Creek.f01 (steady flow) ---

Flow Title=NFF Regression Equation
Program Version=4.00
Number of Profiles=1
Profile Names=P100yr
River Rch & RM=Left Fork Mil...,Main      ,2850.5
582.9883
River Rch & RM=Left Fork Mil...,Main      ,2085
597.0813
River Rch & RM=Left Fork Mil...,Main      ,282.3
661.6711
Boundary for River Rch & Prof#=Left Fork Mil...,Main      ,1
Up Type=0
Dn Type=3
Dn Slope=0.03843

--- Left Fork Mill Creek.g01 (geometry) ---

Geom Title=Geometry
Program Version=4.00

River Reach=Left Fork Mil...     ,Main
Reach XY= 30
     1799644.247      130470.412     1799670.914      130538.185
     1799691.584      130623.455     1799729.280      130706.798
     1799778.649      130764.395     1799859.200      130828.562
     1799943.250      130883.677     1800006.756      130949.199
     1800052.379      131025.465     1800060.798      131050.398
     1800208.658      131228.274     1800226.473      131242.901
     1800267.546      131323.605     1800328.794      131433.132
     1800411.811      131540.138     1800497.157      131715.916
     1800510.509      131732.781     1800560.817      131822.239
     1800589.995      132017.616     1800653.771      132278.359
     1800660.042      132315.357     1800774.111      132483.394
     1800809.087      132558.868     1800829.590      132642.247
     1800850.486      132702.774     1800886.675      132751.783
     1800893.814      132772.926     1800892.669      132847.334
     1800878.503      132890.845     1800866.924      132943.675

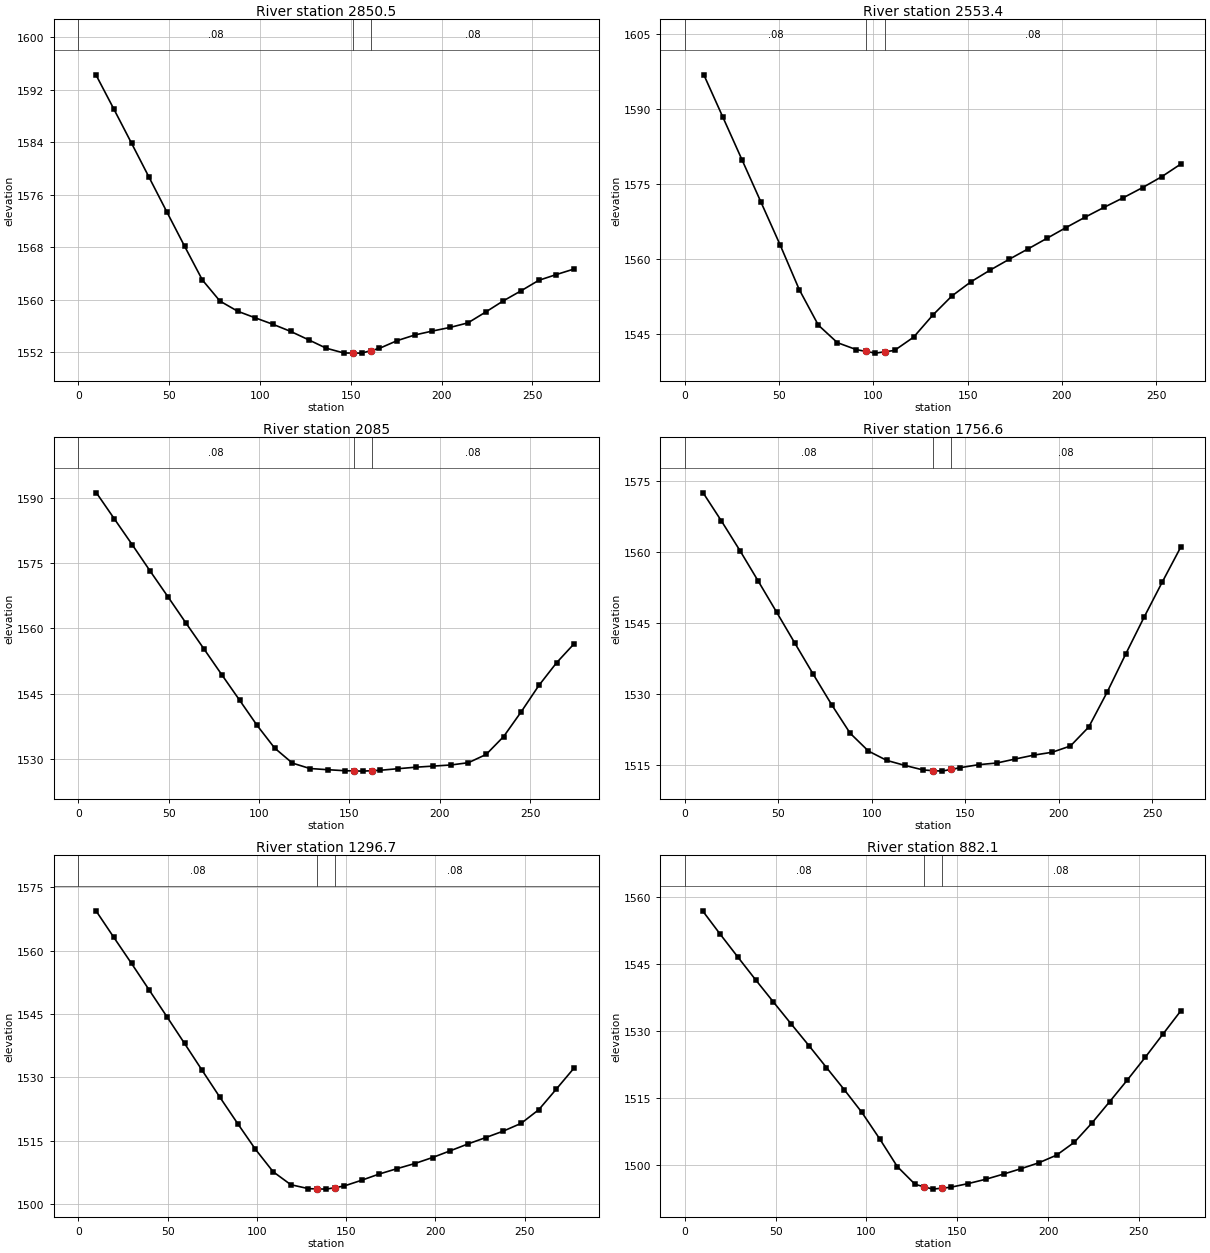
Type RM Length L Ch R = 1 ,2850.5,302.8,297.1,291.5
XS GIS Cut Line= 3
     1799520.103      130528.035     1799647.784      130479.766
     1799775.464      130431.496
#Sta/Elev= 30
     9.7 1594.27    19.5 1589.08    29.3 1583.84    39.0 1578.62    48.7 1573.39
    58.5 1568.14    68.3 1562.99    78.0 1559.77    87.8 1558.22    97.5 1557.21
   107.3 1556.22   117.0 1555.14   126.8 1553.87   136.5 1552.59   146.2 1551.86
     151 1551.85   156.0 1551.84     161 1552.21   165.8 1552.57   175.5 1553.74
   185.3 1554.61   195.0 1555.21   204.7 1555.76   214.5 1556.45   224.2 1558.09
   234.0 1559.81   243.7 1561.33   253.5 1562.94   263.2 1563.82   273.0 1564.67
#Mann= 3 , 0 , 0
       0    0.08       0     151   0.045       0     161    0.08       0
Bank Sta=     151,     161
Exp/Cntr=0.3,0.1

Type RM Length L Ch R = 1 ,2553.4,466.5,468.3,470.2
XS GIS Cut Line= 2
     1799685.587      130807.894     1799896.402      130650.816
#Sta/Elev= 28
    10.1 1596.81    20.2 1588.35    30.3 1579.88    40.4 1571.39    50.6 1562.82
    60.7 1553.94    70.8 1546.86    80.9 1543.36    91.0 1541.96    96.1 1541.61
   101.1 1541.27   106.1 1541.54   111.2 1541.81   121.3 1544.45   131.5 1548.86
   141.6 1552.67   151.7 1555.50   161.8 1557.82   171.9 1559.98   182.0 1562.07
   192.1 1564.20   202.2 1566.34   212.3 1568.41   222.5 1570.40   232.6 1572.30
   242.7 1574.30   252.8 1576.46   262.9 1578.98
#Mann= 3 , 0 , 0
       0    0.08       0    96.1   0.045       0   106.1    0.08       0
Bank Sta=    96.1,   106.1
Exp/Cntr=0.3,0.1

Type RM Length L Ch R = 1 ,2085,330.2,328.5,326.8
XS GIS Cut Line= 3
     1799955.770      131164.366     1800012.144      131123.428
     1800187.135      131017.331
#Sta/Elev= 30
    10.0 1591.12    19.9 1585.15    29.9 1579.15    39.8 1573.10    49.8 1567.10
    59.7 1561.10    69.7 1555.13    79.4 1549.30    89.2 1543.48    98.9 1537.68
   108.6 1532.47   118.4 1529.02   128.1 1527.77   137.9 1527.50   147.6 1527.26
   152.4 1527.22   157.4 1527.17   162.4 1527.27   167.1 1527.37   176.9 1527.73
   186.6 1528.07   196.4 1528.33   206.1 1528.58   215.8 1529.11   225.6 1531.00
   235.3 1535.12   245.1 1540.86   254.8 1546.87   264.6 1552.09   274.3 1556.45
#Mann= 3 , 0 , 0
       0    0.08       0   152.4   0.045       0   162.4    0.08       0
Bank Sta=   152.4,   162.4
Exp/Cntr=0.3,0.1

Type RM Length L Ch R = 1 ,1756.6,457.6,459.9,462.2
XS GIS Cut Line= 2
     1800149.932      131436.206     1800363.503      131279.128
#Sta/Elev= 29
     9.8 1572.46    19.6 1566.51    29.5 1560.26    39.3 1553.80    49.1 1547.27
    58.9 1540.69    68.7 1534.15    78.6 1527.69    88.4 1521.72    98.2 1517.95
   108.0 1515.98   117.8 1514.91   127.6 1513.95   132.5 1513.84   137.5 1513.72
   142.5 1514.09   147.3 1514.45   157.1 1515.08   166.9 1515.44   176.7 1516.28
   186.6 1517.10   196.4 1517.70   206.2 1519.03   216.0 1523.04   225.8 1530.38
   235.7 1538.40   245.5 1546.16   255.3 1553.64   265.1 1560.95
#Mann= 3 , 0 , 0
       0    0.08       0   132.5   0.045       0   142.5    0.08       0
Bank Sta=   132.5,   142.5
Exp/Cntr=0.3,0.1

Type RM Length L Ch R = 1 ,1296.7,409.4,414.6,419.7
XS GIS Cut Line= 2
     1800389.683      131805.478     1800630.811      131667.690
#Sta/Elev= 30
     9.9 1569.44    19.8 1563.20    29.8 1556.97    39.7 1550.68    49.6 1544.37
    59.5 1538.02    69.4 1531.62    79.3 1525.27    89.3 1519.01    99.2 1512.95
   109.1 1507.64   119.0 1504.57   128.9 1503.63   133.9 1503.57   138.9 1503.52
   143.9 1503.89   148.8 1504.25   158.7 1505.63   168.6 1507.11   178.5 1508.37
   188.5 1509.59   198.4 1511.01   208.3 1512.60   218.2 1514.22   228.1 1515.72
   238.0 1517.26   248.0 1519.10   257.9 1522.34   267.8 1527.26   277.7 1532.23
#Mann= 3 , 0 , 0
       0    0.08       0   133.9   0.045       0   143.9    0.08       0
Bank Sta=   133.9,   143.9
Exp/Cntr=0.3,0.1

Type RM Length L Ch R = 1 ,882.1,362.1,360.7,359.4
XS GIS Cut Line= 3
     1800482.223      132168.912     1800613.864      132132.817
     1800745.505      132096.722
#Sta/Elev= 30
     9.8 1556.91    19.5 1551.67    29.3 1546.51    39.0 1541.46    48.8 1536.49
    58.5 1531.61    68.3 1526.75    78.0 1521.82    87.8 1516.86    97.5 1511.77
   107.3 1505.85   117.0 1499.64   126.8 1495.66   131.5 1495.14   136.5 1494.59
   141.5 1494.80   146.3 1495.00   156.0 1495.83   165.8 1496.81   175.5 1497.96
   185.3 1499.19   195.0 1500.50   204.7 1502.20   214.5 1505.09   224.2 1509.41
   234.0 1514.21   243.7 1519.05   253.5 1524.10   263.2 1529.27   273.0 1534.46
#Mann= 3 , 0 , 0
       0    0.08       0   131.5   0.045       0   141.5    0.08       0
Bank Sta=   131.5,   141.5
Exp/Cntr=0.3,0.1

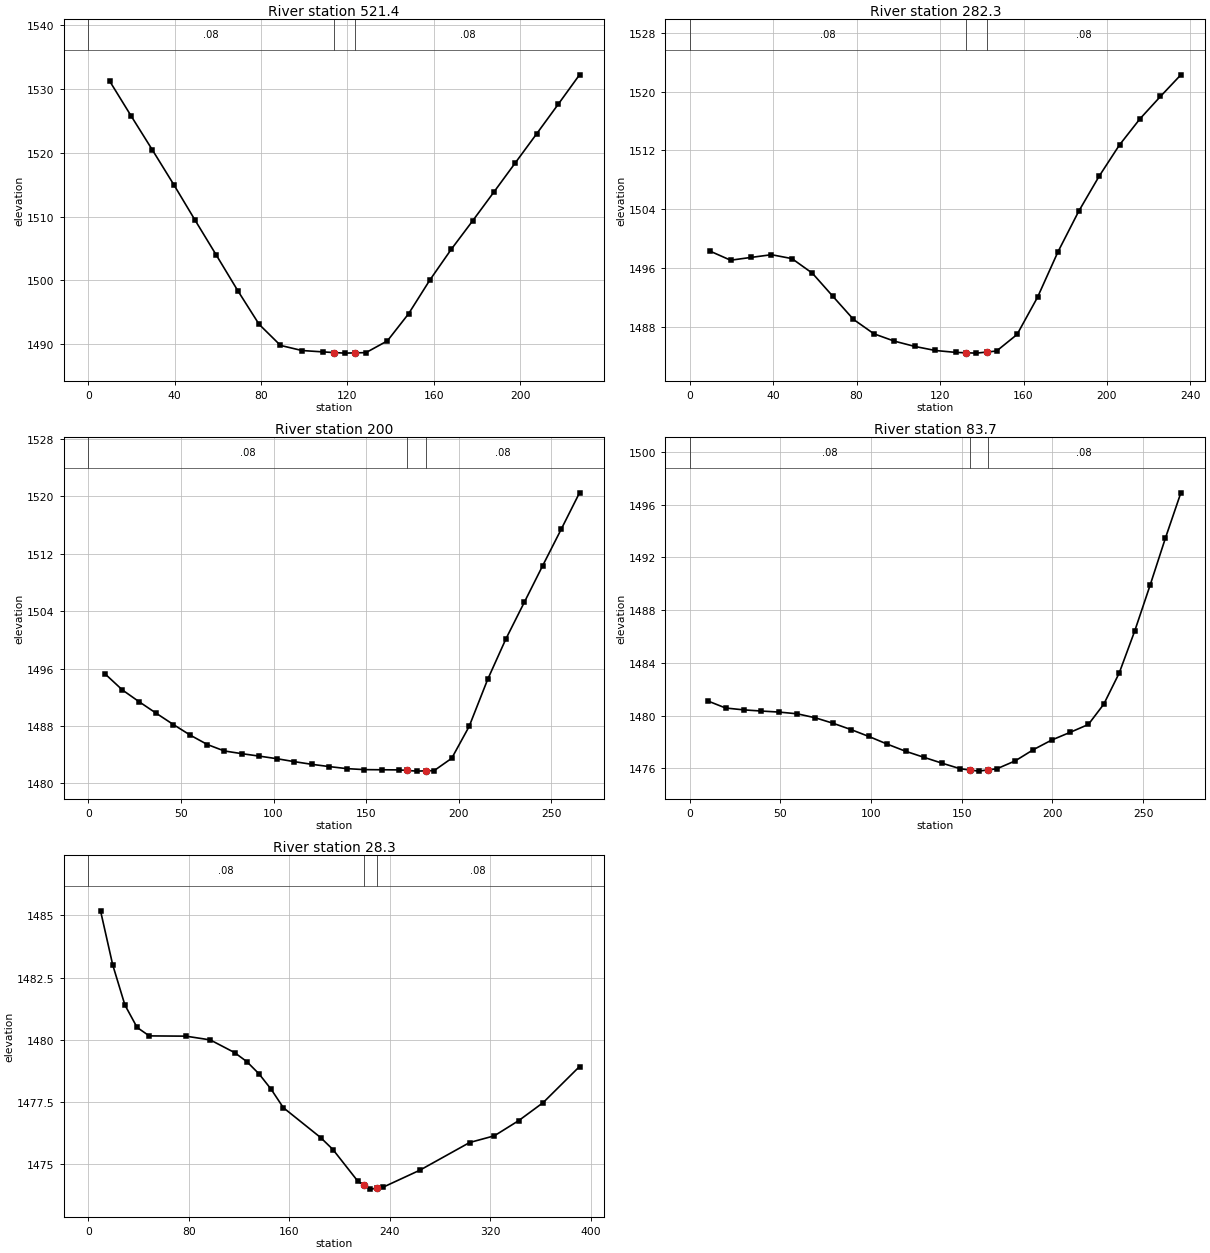
Type RM Length L Ch R = 1 ,521.4,236.8,239.1,241.4
XS GIS Cut Line= 2
     1800643.212      132497.173     1800858.161      132422.767
#Sta/Elev= 25
     9.9 1531.24    19.8 1525.80    29.7 1520.44    39.6 1515.01    49.4 1509.47
    59.3 1503.96    69.2 1498.41    79.1 1493.12    89.0 1489.82    98.9 1489.02
   108.8 1488.80   113.7 1488.70   118.7 1488.61   123.7 1488.65   128.6 1488.69
   138.5 1490.53   148.3 1494.77   158.2 1500.08   168.1 1504.89   178.0 1509.35
   187.9 1513.89   197.8 1518.46   207.7 1523.02   217.6 1527.61   227.5 1532.24
#Mann= 3 , 0 , 0
       0    0.08       0   113.7   0.045       0   123.7    0.08       0
Bank Sta=   113.7,   123.7
Exp/Cntr=0.3,0.1

Type RM Length L Ch R = 1 ,282.3,79.1,82.3,83
XS GIS Cut Line= 2
     1800709.350      132707.988     1800939.456      132658.384
#Sta/Elev= 26
     9.8 1498.27    19.6 1497.04    29.4 1497.42    39.2 1497.79    49.0 1497.26
    58.8 1495.27    68.7 1492.10    78.5 1488.98    88.3 1487.02    98.1 1486.02
   107.9 1485.30   117.7 1484.75   127.5 1484.49   132.3 1484.44   137.3 1484.39
   142.3 1484.53   147.1 1484.68   156.9 1486.93   166.7 1491.99   176.5 1498.18
   186.4 1503.68   196.2 1508.46   206.0 1512.74   215.8 1516.29   225.6 1519.33
   235.4 1522.28
#Mann= 3 , 0 , 0
       0    0.08       0   132.3   0.045       0   142.3    0.08       0
Bank Sta=   132.3,   142.3
Exp/Cntr=0.3,0.1

Type RM Length L Ch R = 1 ,200,115.7,116.3,119.4
XS GIS Cut Line= 4
     1800701.014      132739.230     1800771.113      132761.136
     1800902.548      132747.116     1800950.741      132712.067
#Sta/Elev= 30
     9.2 1495.21    18.4 1493.01    27.5 1491.36    36.7 1489.76    45.9 1488.20
    55.1 1486.71    64.3 1485.41    73.4 1484.52    82.9 1484.14    92.3 1483.80
   101.8 1483.44   111.2 1483.03   120.6 1482.66   130.1 1482.34   139.5 1482.06
   149.0 1481.92   158.4 1481.90   167.9 1481.88   172.3 1481.80   177.3 1481.71
   182.3 1481.75   186.7 1481.78   196.2 1483.50   205.6 1487.93   215.6 1494.48
   225.5 1500.15   235.4 1505.23   245.3 1510.32   255.3 1515.39   265.2 1520.47
#Mann= 3 , 0 , 0
       0    0.08       0   172.3   0.045       0   182.3    0.08       0
Bank Sta=   172.3,   182.3
Exp/Cntr=0.3,0.1

Type RM Length L Ch R = 1 ,83.7,53.1,55.4,57.7
XS GIS Cut Line= 4
     1800744.826      132799.690     1800820.182      132863.655
     1800941.102      132861.903     1800980.533      132829.482
#Sta/Elev= 30
     9.9 1481.11    19.8 1480.57    29.7 1480.43    39.5 1480.34    49.4 1480.26
    59.3 1480.13    69.2 1479.83    79.1 1479.41    89.0 1478.93    98.8 1478.41
   108.9 1477.83   119.0 1477.29   129.1 1476.83   139.2 1476.38   149.2 1475.96
   154.3 1475.87   159.3 1475.78   164.3 1475.87   169.4 1475.96   179.5 1476.56
   189.5 1477.41   199.6 1478.14   209.7 1478.72   219.8 1479.32   228.3 1480.86
   236.8 1483.22   245.3 1486.39   253.8 1489.87   262.3 1493.47   270.8 1496.90
#Mann= 3 , 0 , 0
       0    0.08       0   154.3   0.045       0   164.3    0.08       0
Bank Sta=   154.3,   164.3
Exp/Cntr=0.3,0.1

Type RM Length L Ch R = 1 ,28.3,25.7,28.3,30.8
XS GIS Cut Line= 4
     1800689.425      132807.804     1800806.162      132910.096
     1800973.523      132924.992     1801038.028      132904.256
#Sta/Elev= 25
     9.7 1485.18    19.4 1483.01    29.1 1481.40    38.8 1480.50    48.5 1480.16
    77.6 1480.15    97.0 1480.00   116.4 1479.49   126.1 1479.13   135.8 1478.64
   145.5 1478.02   155.2 1477.28   184.9 1476.08   194.7 1475.60   214.5 1474.33
   219.4 1474.17   224.4 1474.01   229.4 1474.04   234.3 1474.08   263.9 1474.77
   303.5 1475.88   323.2 1476.15   342.6 1476.76   362.0 1477.48   391.0 1478.93
#Mann= 3 , 0 , 0
       0    0.08       0   219.4   0.045       0   229.4    0.08       0
Bank Sta=   219.4,   229.4
Exp/Cntr=0.3,0.1